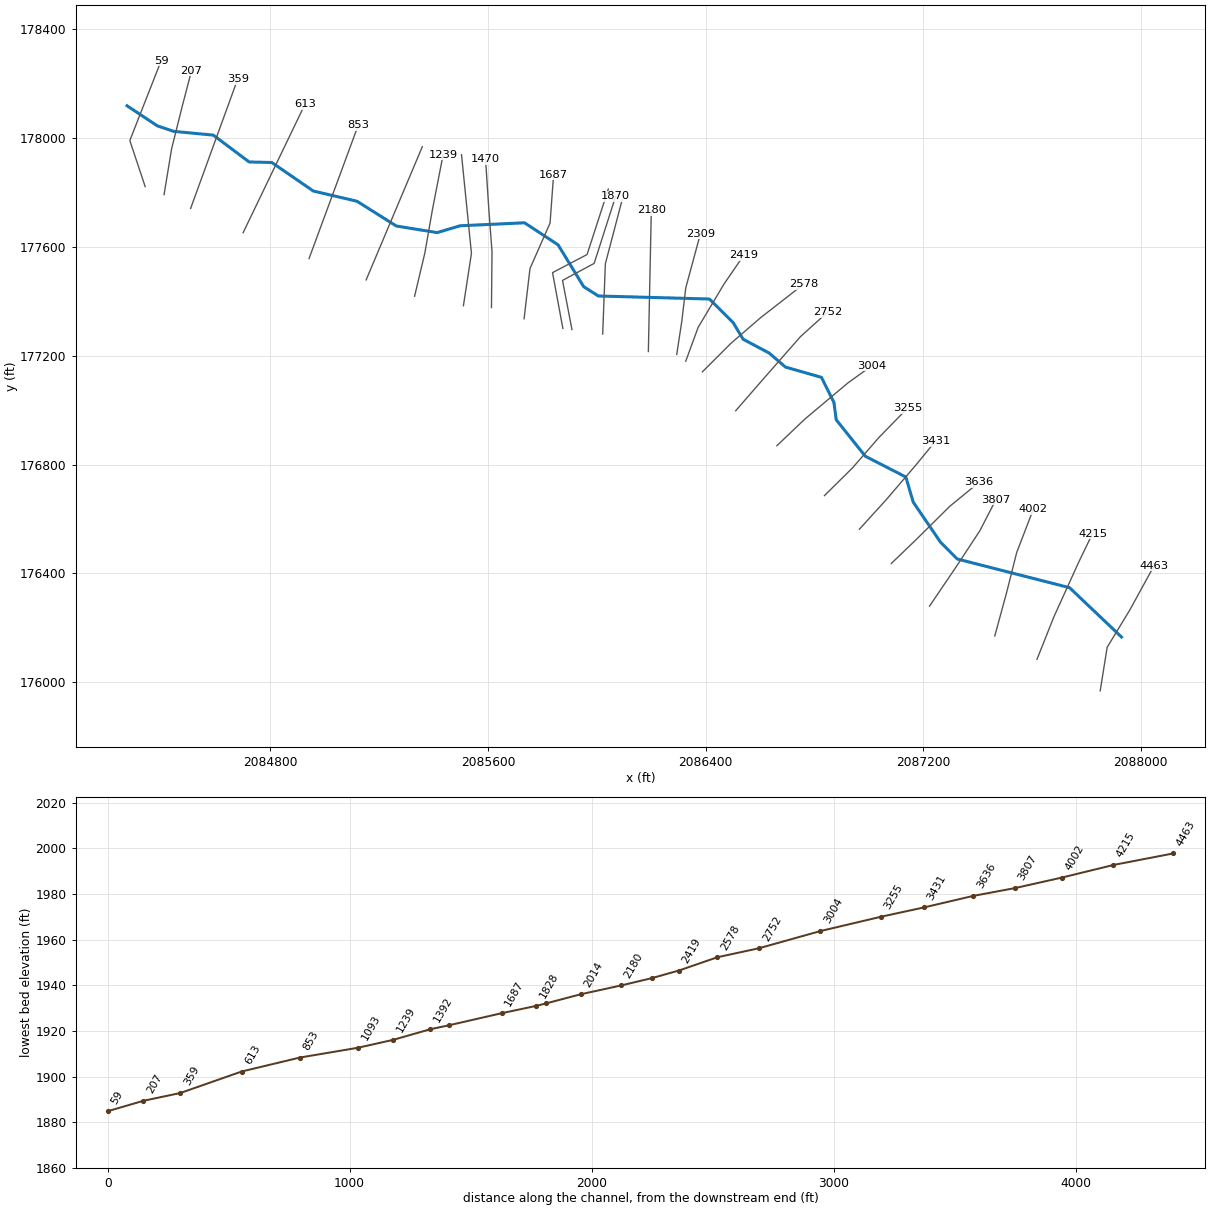
--- WSMNBRCH.prj (project) ---

Proj Title=WSMNBRCH
Current Plan=p01
Default Exp/Contr=0,0
English Units
Geom File=g01
Flow File=f01
Plan File=p01
Background Map Layer=Inundation Boundary (01pct Value_0)
BEGIN DESCRIPTION:
Stream Name: Wiseman Branch
Flood Zone: Approximate
Monroe County, West Virginia
HEC-RAS Version: 5.0.7
Vertical Datum: NAVD88
Projection: NAD 1983 StatePlane West Virginia S FIPS 4702 (US Feet)
LiDAR: 2016, 1-meter
Land Use: 2016 NLCD
Hydrology Method:
Regression.
Model Notes:
END DESCRIPTION:
DSS File=dss
DSS Export Rating Curves= 0
DSS Export Rating Curve Sorted= 0
DSS Export Volume Flow Curves= 0
DXF OffsetX= 0
DXF OffsetY= 0
DXF ScaleX= 0
DXF ScaleY= 0

--- WSMNBRCH.p01 (plan) ---

Plan Title=Floodplain
Program Version=5.07
Short Identifier=Floodplain
Geom File=g01
Flow File=f01
Subcritical Flow
K Sum by GR= 0
Std Step Tol= 0.01
Critical Tol= 0.01
Num of Std Step Trials= 20
Max Error Tol= 0.3
Flow Tol Ratio= 0.001
Split Flow NTrial= 30
Split Flow Tol= 0.02
Split Flow Ratio= 0.02
Log Output Level= 0
Friction Slope Method= 1
Unsteady Friction Slope Method= 2
Unsteady Bridges Friction Slope Method= 1
Parabolic Critical Depth
Global Vel Dist= 0 , 0 , 0
Global Log Level= 0
CheckData=True
Encroach Param=-1 ,0,0, 0
Computation Interval=0.1SEC
Output Interval=1MIN
Instantaneous Interval=Max Profile
Mapping Interval=1HOUR
Computation Time Step Use Courant=        0
Computation Time Step Use Time Series=    0
Computation Time Step Count To Double=0
Computation Time Step Max Doubling=0
Computation Time Step Max Halving=0
Computation Time Step Residence Courant=0
Run HTab= 0
Run UNet= 0
Run Sediment= 0
Run PostProcess= 0
Run WQNet= 0
Run RASMapper=-1
UNET Theta= 0
UNET Theta Warmup= 0
UNET ZTol= 0
UNET ZSATol= 0
UNET MxIter= 0
UNET Max Iter WO Improvement= 0
UNET MaxInSteps= 0
UNET DtIC= 0
UNET DtMin= 0
UNET MaxCRTS= 0
UNET WFStab= 0
UNET SFStab= 0
UNET WFX= 1
UNET SFX= 1
UNET 1D Methodology=Finite Difference
UNET DSS MLevel= 1
UNET Pardiso=0
UNET DZMax Abort= 0
UNET Use Existing IB Tables= 0
UNET Froude Reduction=False
UNET Froude Limit= 0
UNET Froude Power= 0
UNET D1 Cores= 0
UNET D2 Coriolis=0
UNET D2 Cores= 0
UNET D2 Theta= 1
UNET D2 Theta Warmup= 1
UNET D2 Z Tol= 0.01
UNET D2 Volume Tol= 0.01
UNET D2 Max Iterations= 20
UNET D2 Equation= 0
UNET D2 RampUpFraction=0.1
UNET D2 TimeSlices= 1
UNET D2 BCVolumeCheck=0
UNET D1D2 MaxIter= 0
UNET D1D2 ZTol=0.01
UNET D1D2 QTol=0.1
UNET D1D2 MinQTol=1
DSS File=dss
Write IC File= 0
Write IC File at Fixed DateTime=0
Write IC File at Sim End=0
Echo Input=False
Echo Parameters=False
Echo Output=False
Write Detailed= 0
HDF Write Warmup=0
HDF Write Time Slices=0
HDF Flush=0
HDF Face Node Velocities=0
HDF Compression= 1
HDF Chunk Size= 1
HDF Spatial Parts= 1
HDF Use Max Rows=0
HDF Fixed Rows= 1
Calibration Method= 0
Calibration Iterations= 20
Calibration Max Change=0.05
Calibration Tolerance=0.2
Calibration Maximum=1.5
Calibration Minimum=0.5
Calibration Optimization Method= 1
WQ AD Non Conservative
WQ ULTIMATE=-1
WQ Max Comp Step=1HOUR
WQ Output Interval=15MIN
WQ Output Selected Increments= 0
WQ Output face flow=0
WQ Output face velocity=0
WQ Output face area=0
WQ Output face dispersion=0
WQ Output cell volume=0
WQ Output cell surface area=0
WQ Output cell continuity=0
WQ Output cumulative cell continuity=0
WQ Output face conc=0
WQ Output face dconc_dx=0
WQ Output face courant=0
WQ Output face peclet=0
WQ Output face adv mass=0
WQ Output face disp mass=0
WQ Output cell mass=0
WQ Output cell source sink temp=0
WQ Output nsm pathways=0
WQ Output nsm derived pathways=0
WQ Output MaxMinRange=-1
WQ Daily Max Min Mean=-1
WQ Daily Range=0
WQ Daily Time=0
WQ Create Restart=0
WQ Fixed Restart=0
WQ System Summary=0
WQ Write To DSS=0
WQ Use Fixed Temperature=0
Sorting and Armoring Iterations= 10
XS Update Threshold= 0.02
Bed Roughness Predictor= 0
Hydraulics Update Threshold= 0.02
Energy Slope Method= 1
Volume Change Method= 1
Sediment Retention Method= 0
XS Weighting Method= 0
Number of US Weighted Cross Sections= 1
Number of DS Weighted Cross Sections= 1
Upstream XS Weight=0
Main XS Weight=1
Downstream XS Weight=0
Number of DS XS's Weighted with US Boundary= 1
Upstream Boundary Weight= 1
Weight of XSs Associated with US Boundary= 0
Number of US XS's Weighted with DS Boundary= 1
Downstream Boundary Weight= 0.5
Weight of XSs Associated with DS Boundary= 0.5
Percentile Method= 0
Sediment Output Level= 3
Mass or Volume Output= 0
Output Increment Type= 1
Profile and TS Output Increment= 1
XS Output Flag= 0
XS Output Increment= 10
Write Gradation File= 0
Read Gradation Hotstart= 0
Write HDF5 File= 1
Write Binary Output= 1
Write DSS Sediment File= 0
SV Curve= 0
Specific Gage Flag= 0

--- WSMNBRCH.f01 (steady flow) ---

Flow Title=Flow
Program Version=5.07
Number of Profiles= 6
Profile Names=01pct,10pct,04pct,02pct,0_2pct,01plus
River Rch & RM=WSMNBRCH,Main            ,4463
     554     293     389     469     775     820
River Rch & RM=WSMNBRCH,Main            ,2180
     575     304     404     487     803     850
Boundary for River Rch & Prof#=WSMNBRCH,Main            , 1
Up Type= 0
Dn Type= 3
Dn Slope=0.03055
Boundary for River Rch & Prof#=WSMNBRCH,Main            , 2
Up Type= 0
Dn Type= 3
Dn Slope=0.03055
Boundary for River Rch & Prof#=WSMNBRCH,Main            , 3
Up Type= 0
Dn Type= 3
Dn Slope=0.03055
Boundary for River Rch & Prof#=WSMNBRCH,Main            , 4
Up Type= 0
Dn Type= 3
Dn Slope=0.03055
Boundary for River Rch & Prof#=WSMNBRCH,Main            , 5
Up Type= 0
Dn Type= 3
Dn Slope=0.03055
Boundary for River Rch & Prof#=WSMNBRCH,Main            , 6
Up Type= 0
Dn Type= 3
Dn Slope=0.03055
DSS Import GetInterval= 0
DSS Import GetPeak= 0
DSS Import FillOption= 0

--- WSMNBRCH.g01 (geometry) ---

Geom Title=Geometry
Program Version=5.07

River Reach=WSMNBRCH        ,Main
Reach XY= 30
2087929.10403326176166.1023717642087738.22678577176347.350155871
2087325.19976165 176452.790611412087264.04182167176514.161035449
2087163.54085695176661.631523192 2087136.2570899176754.189112688
2086987.32380701176830.4462984052086880.34226223176964.515873895
2086872.05352287177027.7175114992086826.12009226177120.275100996
2086693.50026253177158.2651563862086633.75226633177209.724413233
2086538.08639957177260.492941801 2086501.1324366177321.967758705
2086414.10067334177408.308793683     2086005.775      177419.471
     2085951.639       177453.88     2085857.589      177607.572
     2085734.284      177688.527     2085497.453      177677.534
     2085412.756      177652.415     2085262.756      177676.721
     2085118.312      177767.693     2084957.895      177805.193
     2084805.117      177910.054     2084721.784      177912.138
     2084589.839      178010.749     2084444.006      178024.638
     2084384.284      178044.777      2084272.68      178118.643

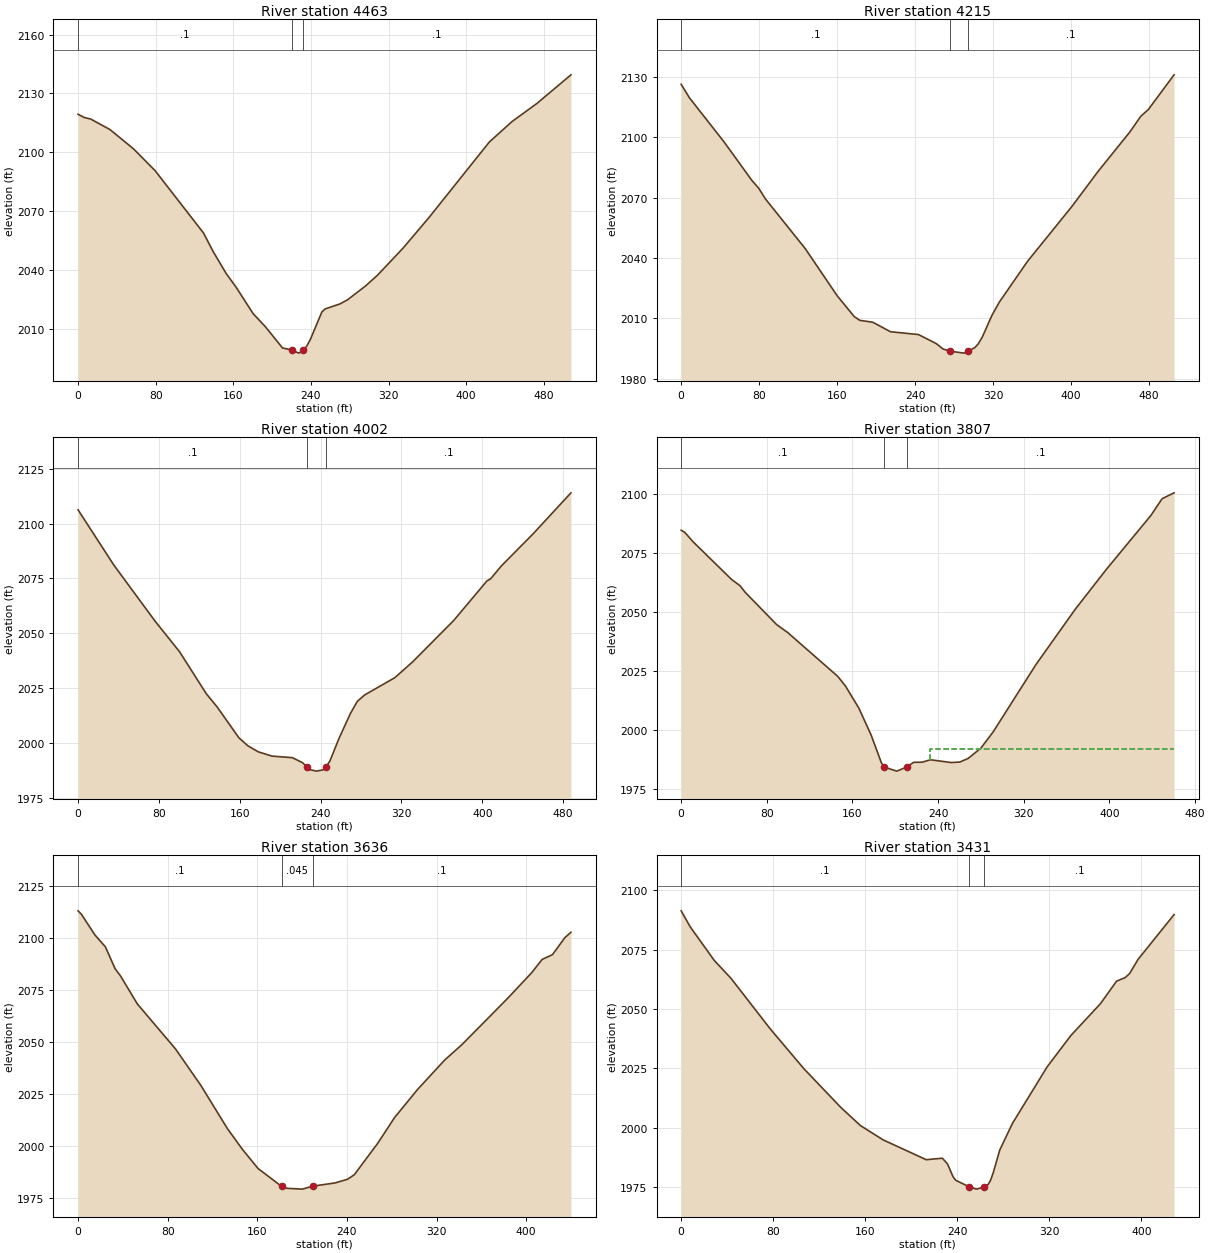
Type RM Length L Ch R = 1 ,4463    ,242.6,248,246.5
XS GIS Cut Line= 4
2087850.91184146175968.0349404072087876.59133316176128.226055304
2087959.74397296176265.1833443762088049.01077744176427.820125148
#Sta/Elev= 30
       0 2119.43     6.4 2117.77      13 2116.99    32.9 2111.64    57.2  2101.8
    79.5 2090.65   129.3 2058.96   139.3 2049.46   152.6 2038.37     163 2031.29
   180.4 2017.93   193.3 2011.12   210.7 2000.44   220.1 1999.38   227.5  1997.8
   232.2 1999.15   235.5 2001.25   239.4 2004.73   251.3 2018.79   254.7 2020.31
     270 2022.87   277.6  2024.9   296.4 2032.04   308.7 2037.52     335 2051.29
   361.2 2066.55   423.9 2105.31   447.2 2115.68   472.8 2124.88507.9845  2139.5
#Mann= 3 ,-1 , 0
       0      .1       0   220.1    .045       0   232.2      .1       0
Bank Sta=220.1,232.2
XS Rating Curve= 0 ,0
Exp/Cntr(USF)=0,0
Exp/Cntr=0.3,0.1

Type RM Length L Ch R = 1 ,4215    ,209.1,212.1,214.2
XS GIS Cut Line= 4
2087618.57358322176084.2040695312087680.93806306176240.726685613
2087771.42770048 176440.048454532087822.78668389176546.434920148
#Sta/Elev= 30
       0 2126.28     8.5 2119.55    44.2 2097.52    72.4 2078.59    79.5 2074.66
    86.5 2069.28   127.2 2044.68     160 2021.24   177.5 2010.89   183.2 2009.03
   196.6 2008.06   214.7 2003.36   243.4 2001.95   261.4 1997.53   268.6 1994.78
   275.8 1993.68   290.3 1992.73   294.3 1993.64   301.1 1995.47   304.7 1997.34
   308.9 2000.77   318.8 2011.56   326.3 2018.06   355.1 2038.25   400.5 2065.44
   427.6    2083   460.4 2102.72   471.3 2110.35   479.1 2113.73505.5249 2130.98
#Mann= 3 ,-1 , 0
       0      .1       0   275.8    .045       0   294.3      .1       0
Bank Sta=275.8,294.3
XS Rating Curve= 0 ,0
Exp/Cntr(USF)=0,0
Exp/Cntr=0.3,0.1

Type RM Length L Ch R = 1 ,4002    ,199.8,195.2,189.6
XS GIS Cut Line= 4
2087463.27380007176169.8023752012087506.07295291176326.324991283
2087543.98077399176476.733442674 2087605.1224209176635.701724632
#Sta/Elev= 30
       0 2106.23    35.4 2081.07    76.2 2055.55   100.5 2041.55   126.9 2022.47
   137.5 2016.54   159.2 2002.38     168 1998.78   178.2 1996.04   191.9 1994.07
     212 1993.36   222.2 1991.06   226.8 1988.92   228.9 1987.98   235.7 1987.23
   242.5 1987.81   245.7  1989.3   249.2 1991.84   258.3 2002.24   269.5  2013.5
   276.3 2018.98   283.5 2021.89   313.5 2029.81     331 2036.96   371.9 2055.94
   404.5 2073.81   408.3 2074.85   418.8 2080.66   450.5 2095.41487.7014 2113.97
#Mann= 3 ,-1 , 0
       0      .1       0   226.8    .045       0   245.7      .1       0
Bank Sta=226.8,245.7
XS Rating Curve= 0 ,0
Exp/Cntr(USF)=0,0
Exp/Cntr=0.3,0.1

Type RM Length L Ch R = 1 ,3807    ,174,171.1,167.4
XS GIS Cut Line= 4
 2087223.5985442176279.8573396332087318.97951337 176420.48312752
2087408.24631786176556.2175836532087466.94229889  176669.9410469
#Sta/Elev= 30
       0 2084.75     3.4 2083.82    11.4 2079.72      47 2063.91      55  2061.2
    59.9 2058.37    89.2 2044.72    99.5 2041.36   146.2  2022.8   153.5 2018.65
     166 2009.26   177.5 1997.81   186.9 1986.23   189.6  1984.3   201.4 1982.59
   210.6 1984.31   217.1 1986.33   224.9 1986.37   232.8  1987.4   252.4 1986.23
   260.3 1986.44   268.1 1987.99   279.9 1992.33   291.2 1999.09   331.4 2027.81
   367.9 2051.14   397.5 2068.36   438.6 2090.95   449.2 2098.12460.3559 2100.61
#Mann= 3 ,-1 , 0
       0      .1       0   189.6    .045       0   210.6      .1       0
#XS Ineff= 2 , 0
                          232.05         1991.94
Permanent Ineff=
       F       F
Bank Sta=189.6,210.6
XS Rating Curve= 0 ,0
Exp/Cntr(USF)=0,0
Exp/Cntr=0.3,0.1

Type RM Length L Ch R = 1 ,3636    ,204.2,205.2,203.7
XS GIS Cut Line= 4
2087082.97275631176436.3799557152087175.90805961  176525.6467602
2087298.19135342176646.7072210762087405.80065198176734.751192622
#Sta/Elev= 30
       0 2112.97       3 2111.32      15 2101.41    24.4 2095.65    33.1 2085.12
    37.8 2081.75    52.9 2068.23      87 2046.59   109.7 2028.98   133.3  2008.3
   146.8 1998.26   160.7  1989.1   181.6 1980.56   186.3  1979.6   200.2  1979.2
   209.5 1980.62   229.5 1982.19   240.6 1983.95   246.6 1986.14   267.5 2001.23
   282.5 2013.58   303.1 2027.13   327.1 2041.16   342.7 2048.68   383.9 2071.15
   404.9 2083.22   414.2 2089.58   423.5 2091.92   434.5 2100.05439.9724 2102.68
#Mann= 3 ,-1 , 0
       0      .1       0   181.6    .045       0   209.5      .1       0
Bank Sta=181.6,209.5
XS Rating Curve= 0 ,0
Exp/Cntr(USF)=0,0
Exp/Cntr=0.3,0.1

Type RM Length L Ch R = 1 ,3431    ,176.7,175.8,174.2
XS GIS Cut Line= 4
2086965.58079425176562.3317483442087064.63026224176671.163879839
2087173.46239373176798.3385054052087245.60953708176886.382476951
#Sta/Elev= 30
       0 2091.29     7.9 2084.51    28.8 2070.38    43.3 2062.86    77.5 2041.53
   106.7 2024.79   138.6 2008.58   155.8 2000.87   175.6 1994.83     213  1986.5
     227 1987.13   231.5 1984.69   236.3 1979.32   238.6 1977.84   250.3 1975.09
   256.7 1974.11   263.6 1974.99   266.8 1976.07   268.9 1977.84   271.2 1980.98
   276.9 1990.59   287.9 2001.78   318.1 2025.62   338.7  2038.8   364.4  2052.2
   378.4 2061.67     386 2063.21   389.8 2064.92     397 2070.79 428.371  2089.7
#Mann= 3 ,-1 , 0
       0      .1       0   250.3    .045       0   263.6      .1       0
Bank Sta=250.3,263.6
XS Rating Curve= 0 ,0
Exp/Cntr(USF)=0,0
Exp/Cntr=0.3,0.1

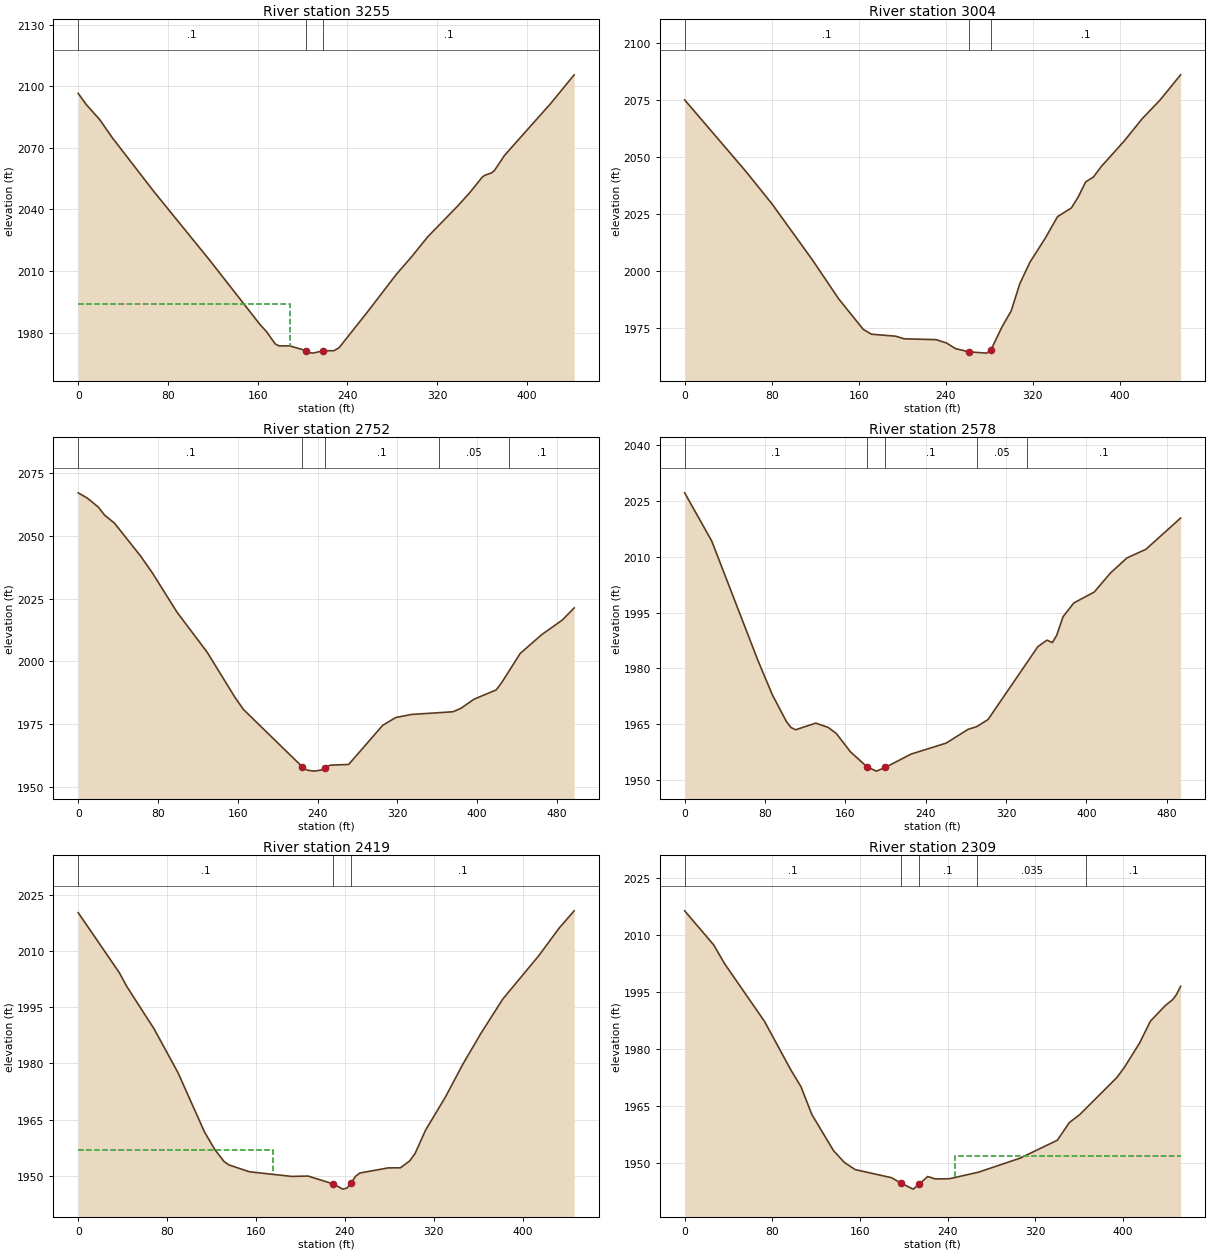
Type RM Length L Ch R = 1 ,3255    ,253.2,251.4,246.7
XS GIS Cut Line= 4
2086837.18333574176685.8378750962086939.90130255176787.333008962
 2087037.7279376176899.8336392712087141.66873734177006.220104889
#Sta/Elev= 30
       0 2096.46     7.3 2090.98    19.3 2083.64    30.5 2074.83    67.6 2048.62
   117.3 2015.25   162.6 1983.64   167.5 1980.82   175.7 1974.54   179.1 1973.61
   188.7 1973.59     203 1971.31   206.1 1970.29   209.3 1970.07   218.6 1971.24
     228 1971.24   232.6 1972.69   258.2  1990.3   283.7 2008.44   297.8  2017.3
   311.4 2026.53   338.9 2041.98   349.4 2048.34   360.3 2055.74   362.6 2056.63
   368.2  2057.7     371 2058.83   380.2 2066.35   421.5 2091.69442.2223 2105.51
#Mann= 3 ,-1 , 0
       0      .1       0     203    .045       0   218.6      .1       0
#XS Ineff= 2 , 0
          188.98 1994.21
Permanent Ineff=
       F       F
Bank Sta=203,218.6
XS Rating Curve= 0 ,0
Exp/Cntr(USF)=0,0
Exp/Cntr=0.3,0.1

Type RM Length L Ch R = 1 ,3004    ,253.2,252,248.1
XS GIS Cut Line= 4
2086662.31822559176869.2628158172086765.03619239176967.089450869
2086924.00447435177100.3782411262087010.82561296177162.742720971
#Sta/Elev= 30
       0 2074.85    55.9  2043.7    80.2 2029.32   117.3  2004.8   141.8  1987.5
   164.3 1974.17   171.9 1972.07   194.1  1971.2   201.9 1970.05   231.3 1969.68
   240.9 1968.21     249 1965.78   261.3 1964.33   277.9 1963.77   281.8 1965.25
   291.8 1975.19   300.4 1982.32   308.2 1994.14   317.5 2003.57   331.5 2014.04
     343 2023.65   355.7 2027.45   361.9 2032.18   368.9  2038.9     376 2041.02
     383 2045.49   404.3 2056.81   420.6 2066.45   437.1 2074.69   456.2 2085.84
#Mann= 3 ,-1 , 0
       0      .1       0   261.3    .045       0   281.8      .1       0
Bank Sta=261.3,281.8
XS Rating Curve= 0 ,0
Exp/Cntr(USF)=0,0
Exp/Cntr=0.3,0.1

Type RM Length L Ch R = 1 ,2752    ,173.5,173.6,169.4
XS GIS Cut Line= 4
2086510.68694126176997.6602743222086617.07340688177119.943568137
 2086749.1393642177270.3520195282086849.41166513 177360.84165695
#Sta/Elev= 30
       0 2067.08     9.1 2064.99    20.1 2061.43    26.4 2058.22    36.4 2054.99
    62.7 2041.84    74.3 2035.24    99.1 2019.56   129.4 2003.58   156.9 1985.84
   165.6 1980.87   224.7 1958.01   229.3 1956.71   236.3 1956.29   243.3 1956.68
   247.2 1957.55   252.6 1958.66   271.2 1958.95   305.3 1974.52   318.4 1977.63
     334 1978.85   375.8 1979.92   383.8  1981.3     397 1984.95   419.1 1988.61
   424.6 1991.49   443.2 2003.14   464.9 2010.66   485.4 2016.43497.3107 2021.26
#Mann= 5 ,-1 , 0
       0      .1       0   224.7    .045       0   247.2      .1       0
  362.08     .05       0  432.24      .1       0
Bank Sta=224.7,247.2
XS Rating Curve= 0 ,0
Exp/Cntr(USF)=0,0
Exp/Cntr=0.3,0.1

Type RM Length L Ch R = 1 ,2578    ,153.1,159.3,161.8
XS GIS Cut Line= 4
2086388.40364745177140.7317280852086492.34444719177244.672527827
2086601.17657868177338.8306640642086761.36769358177463.559623754
#Sta/Elev= 30
       0 2027.25      27 2014.24    72.6 1982.35    87.3 1972.87   101.3 1965.67
   105.9 1964.05   110.5 1963.44   130.6 1965.23     143 1964.06     151 1962.45
     165 1957.53   181.7 1953.43     191  1952.3   199.7 1953.29   225.7 1956.91
   260.4 1959.84   282.1 1963.53   290.9 1964.29   302.1 1966.19   351.8 1985.84
   360.8 1987.57   366.2 1986.92   370.5 1988.86   376.8 1993.87   387.5 1997.58
   407.9 2000.53   423.8 2005.59   440.5 2009.72   459.4 2012.05493.9283 2020.46
#Mann= 5 ,-1 , 0
       0      .1       0   181.7    .045       0   199.7      .1       0
   290.9     .05       0   340.9      .1       0
Bank Sta=181.7,199.7
XS Rating Curve= 0 ,0
Exp/Cntr(USF)=0,0
Exp/Cntr=0.3,0.1

Type RM Length L Ch R = 1 ,2419    ,100.4,109.6,113
XS GIS Cut Line= 4
2086327.06806279177179.8623821052086372.62738579  177304.1150812
2086467.88778843177463.5727117052086540.36852956177569.187505936
#Sta/Elev= 30
       0 2020.23    36.9 2004.27    43.6  2000.6    68.3 1989.21    89.7 1977.59
   113.7 1961.67   122.9 1957.03   131.2 1953.85   135.5 1952.94     154  1951.1
   192.2 1949.86   206.8 1949.96   228.8 1947.92   238.1 1946.47   241.9 1946.77
   245.5  1948.1   249.6 1949.92   253.4 1950.77     279 1952.14   289.9 1952.16
   298.2 1953.99   303.1 1955.99   312.5 1962.21   330.3 1971.01   346.2 1979.88
   362.1 1987.94     382  1997.2   414.1 2008.66   432.9  2016.2446.1806 2020.73
#Mann= 3 ,-1 , 0
       0      .1       0   228.8    .045       0   245.5      .1       0
#XS Ineff= 2 , 0
          175.34 1956.96
Permanent Ineff=
       F       F
Bank Sta=228.8,245.5
XS Rating Curve= 0 ,0
Exp/Cntr(USF)=0,0
Exp/Cntr=0.3,0.1

Type RM Length L Ch R = 1 ,2309    ,127.5,128.8,130.2
XS GIS Cut Line= 4
2086293.93400969177204.7129219242086312.57191456177326.894742701
2086327.06806279177449.0765634772086380.91089906177647.880882029
#Sta/Elev= 30
       0 2016.29    26.5 2007.34    36.4 2002.42    72.9 1987.24    96.7  1974.6
   106.1 1970.12   116.1 1962.78   135.9 1953.28   145.8  1950.2   155.7 1948.32
   188.8  1946.2   197.8  1944.7   208.6  1943.2   214.2 1944.56   221.8 1946.51
   228.9 1945.87   241.6 1945.93   268.1 1947.65   306.1 1951.33   340.1 1956.04
     351 1960.67   360.5 1962.77   394.5 1972.53   401.3 1975.19   415.2 1981.59
     425 1987.31   438.6 1991.41   445.4 1992.98   448.8 1994.31452.6005 1996.45
#Mann= 5 ,-1 , 0
       0      .1       0   197.8    .045       0   214.2      .1       0
  266.63    .035       0  366.63      .1       0
#XS Ineff= 2 , 0
                          247.14          1951.9
Permanent Ineff=
       F       F
Bank Sta=197.8,214.2
XS Rating Curve= 0 ,0
Exp/Cntr(USF)=0,0
Exp/Cntr=0.3,0.1

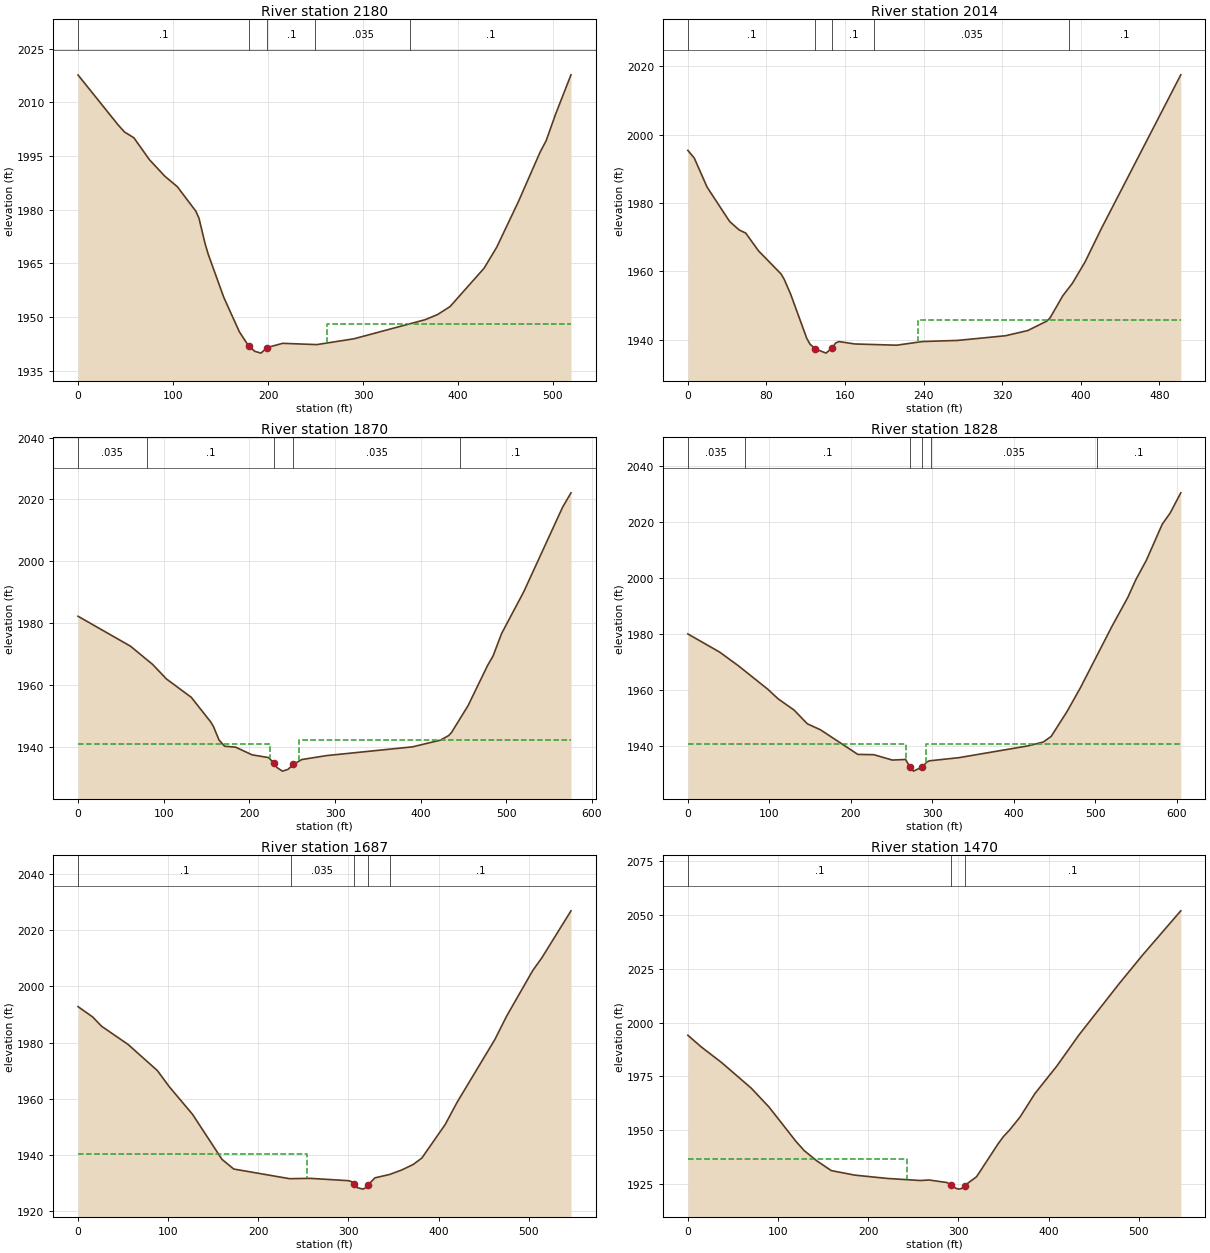
Type RM Length L Ch R = 1 ,2180    ,167.4,166.9,166.8
XS GIS Cut Line= 2
     2086189.575      177215.262     2086200.462      177734.193
#Sta/Elev= 30
       0 2017.63    42.4 2003.62      49  2001.7    58.8 2000.09    75.1 1993.99
    91.4 1989.35   104.5 1986.44     124  1979.6   127.3 1977.65   133.8 1970.47
   137.1 1967.53   153.4 1955.55   169.8 1945.92   179.5 1941.97   186.1 1940.44
   192.6 1939.94   199.1 1941.49   215.4 1942.68   251.4 1942.32   290.5 1943.95
   365.6 1949.29   378.7 1950.74   391.7 1952.95   427.6 1963.69   440.7 1969.47
   463.6 1982.23   486.4 1996.03   492.9 1999.31   502.7 2006.62     519 2017.68
#Mann= 5 ,-1 , 0
       0      .1       0   179.5    .045       0   199.1      .1       0
     250    .035       0     350      .1       0
#XS Ineff= 2 , 0
                          262.18         1948.04
Permanent Ineff=
       F       F
Bank Sta=179.5,199.1
XS Rating Curve= 0 ,0
Exp/Cntr=0.3,0.1

Type RM Length L Ch R = 1 ,2014    ,160.9,143.3,125.9
XS GIS Cut Line= 3
     2086021.722      177279.679     2086031.488      177537.926
     2086093.337      177773.386
#Sta/Elev= 30
       0 1995.44     6.5 1993.21    19.6 1984.68    42.5 1974.64    52.3 1972.13
    58.9 1971.24      72 1966.01    94.9 1959.26    98.1  1957.7   104.7 1953.32
     121 1940.47   124.3 1938.74   129.7 1937.34   140.7 1936.08   147.2  1937.7
   150.5 1939.05   153.8 1939.47   170.1 1938.76   212.6  1938.4   238.8 1939.47
   274.7  1939.8   323.4 1941.17   346.1 1942.69   365.6 1945.47   368.8  1946.4
   381.8 1952.88   391.5  1956.5   404.5 1962.81   420.7 1972.35   501.9 2017.56
#Mann= 5 ,-1 , 0
       0      .1       0   129.7    .045       0   147.2      .1       0
     190    .035       0  388.43      .1       0
#XS Ineff= 2 , 0
                          234.67         1945.69
Permanent Ineff=
       F       F
Bank Sta=129.7,147.2
XS Rating Curve= 0 ,0
Exp/Cntr=0.5,0.3

Type RM Length L Ch R = 1 ,1870    ,42.1,41.9,41.8
XS GIS Cut Line= 4
     2085908.658      177296.172     2085873.936      177476.728
     2085990.255      177539.228     2086069.465      177786.407
#Sta/Elev= 30
       0  1982.2    61.3 1972.49    87.1  1966.6   103.2  1961.9   132.2 1955.96
   154.8 1948.02   158.1  1946.5   164.5  1942.2     171 1940.13   183.9 1939.84
   203.2 1937.34   222.5 1936.45     229 1934.54   232.2 1933.23   238.6 1932.07
   245.1 1932.63   251.5 1934.27   261.2 1935.82   290.2  1937.1   390.5 1939.93
     423 1942.09   432.7 1943.58     436 1944.56   455.4 1953.29   478.1 1966.26
   484.6 1969.38   494.4 1976.56   520.3 1990.09   565.7 2017.49   575.5 2022.15
#Mann= 5 ,-1 , 0
       0    .035       0      80      .1       0     229    .045       0
   251.5    .035       0  445.91      .1       0
#XS Ineff= 2 , 0
          224.36 1940.94  257.88         1942.12
Permanent Ineff=
       F       F
Bank Sta=229,251.5
XS Rating Curve= 0 ,0
Exp/Cntr=0.5,0.3

Type RM Length L Ch R = 1 ,1828    ,130.5,141.5,151.4
XS GIS Cut Line= 4
     2085875.238      177300.296      2085837.26      177505.374
     2085964.214       177571.78     2086042.339      177812.448
#Sta/Elev= 30
       0 1979.93    39.1 1973.43    61.9 1968.59    97.8 1960.26   110.8 1956.76
   130.4 1952.75   146.6 1947.86   162.9 1945.69   208.6 1936.93   228.1 1936.83
   250.9 1934.91   267.2 1935.12   272.7 1932.34   276.9 1930.96   287.7 1932.44
   293.2 1934.21   296.5 1934.64   332.3 1935.75   416.7 1939.93   436.2 1941.34
   445.9 1943.37   465.4 1952.27   481.6 1960.64   520.5 1982.66     540 1993.01
   549.7 1999.26   562.7 2006.24   582.2 2019.11   591.9 2023.09   604.9 2030.29
#Mann= 6 ,-1 , 0
       0    .035       0      70      .1       0   272.7    .045       0
   287.7      .1       0  298.56    .035       0  501.84      .1       0
#XS Ineff= 2 , 0
          267.59 1940.65  292.26         1940.49
Permanent Ineff=
       F       F
Bank Sta=272.7,287.7
XS Rating Curve= 0 ,0
Exp/Cntr=0.5,0.3

Type RM Length L Ch R = 1 ,1687    ,208,216.4,223.3
XS GIS Cut Line= 4
      2085732.66      177335.886     2085754.361      177520.348
     2085828.146      177687.448     2085841.167        177865.4
#Sta/Elev= 30
       0 1992.82    16.3 1989.12    26.1 1985.83    55.4 1979.37      88 1970.03
     101 1964.36   127.1 1954.39   159.7 1938.38   172.7 1934.94   234.7  1931.5
   257.5 1931.62   299.9 1930.79   303.2 1930.49   306.4 1929.48   309.7 1928.31
   316.2 1927.78   319.5 1928.39   322.1  1929.4   329.3  1931.8   345.6 1933.01
   358.6 1934.54   371.6 1936.53   381.4 1938.87   407.3 1950.83   420.3 1958.63
   462.5 1981.18   475.5 1989.49   504.6  2005.8   514.4 2010.18   546.8 2026.97
#Mann= 5 ,-1 , 0
       0      .1       0  235.73    .035       0   306.4    .045       0
   322.1    .035       0  345.73      .1       0
#XS Ineff= 2 , 0
          253.58 1940.24
Permanent Ineff=
       F       F
Bank Sta=306.4,322.1
XS Rating Curve= 0 ,0
Exp/Cntr=0.3,0.1

Type RM Length L Ch R = 1 ,1470    ,78.3,78.5,79.1
XS GIS Cut Line= 4
2085612.71959716177377.006641209 2085614.6963275177582.586596663
2085602.83594546177740.7250239362085590.97556341  177922.5842153
#Sta/Elev= 30
       0 1994.08    14.6 1988.73    37.6 1981.32    70.4 1969.42    90.1 1960.63
   119.9 1944.69     129 1940.43   142.6 1935.78     159 1931.13   185.2 1929.02
   221.4 1927.48   257.6 1926.53   267.4 1926.76   287.2 1925.59   291.7 1924.41
     297 1922.93   300.3 1922.52   303.6 1922.84   306.8 1924.16   320.1 1928.31
   343.8 1943.52   349.7  1946.9   356.6 1949.99   368.3 1956.09   384.8    1967
   408.9 1979.68   433.1 1993.97   477.9 2017.96   504.2 2031.43   546.4 2051.93
#Mann= 3 ,-1 , 0
       0      .1       0   291.7    .045       0   306.8      .1       0
#XS Ineff= 2 , 0
          243.27 1936.75
Permanent Ineff=
       F       F
Bank Sta=291.7,306.8
XS Rating Curve= 0 ,0
Exp/Cntr(USF)=0,0
Exp/Cntr=0.3,0.1

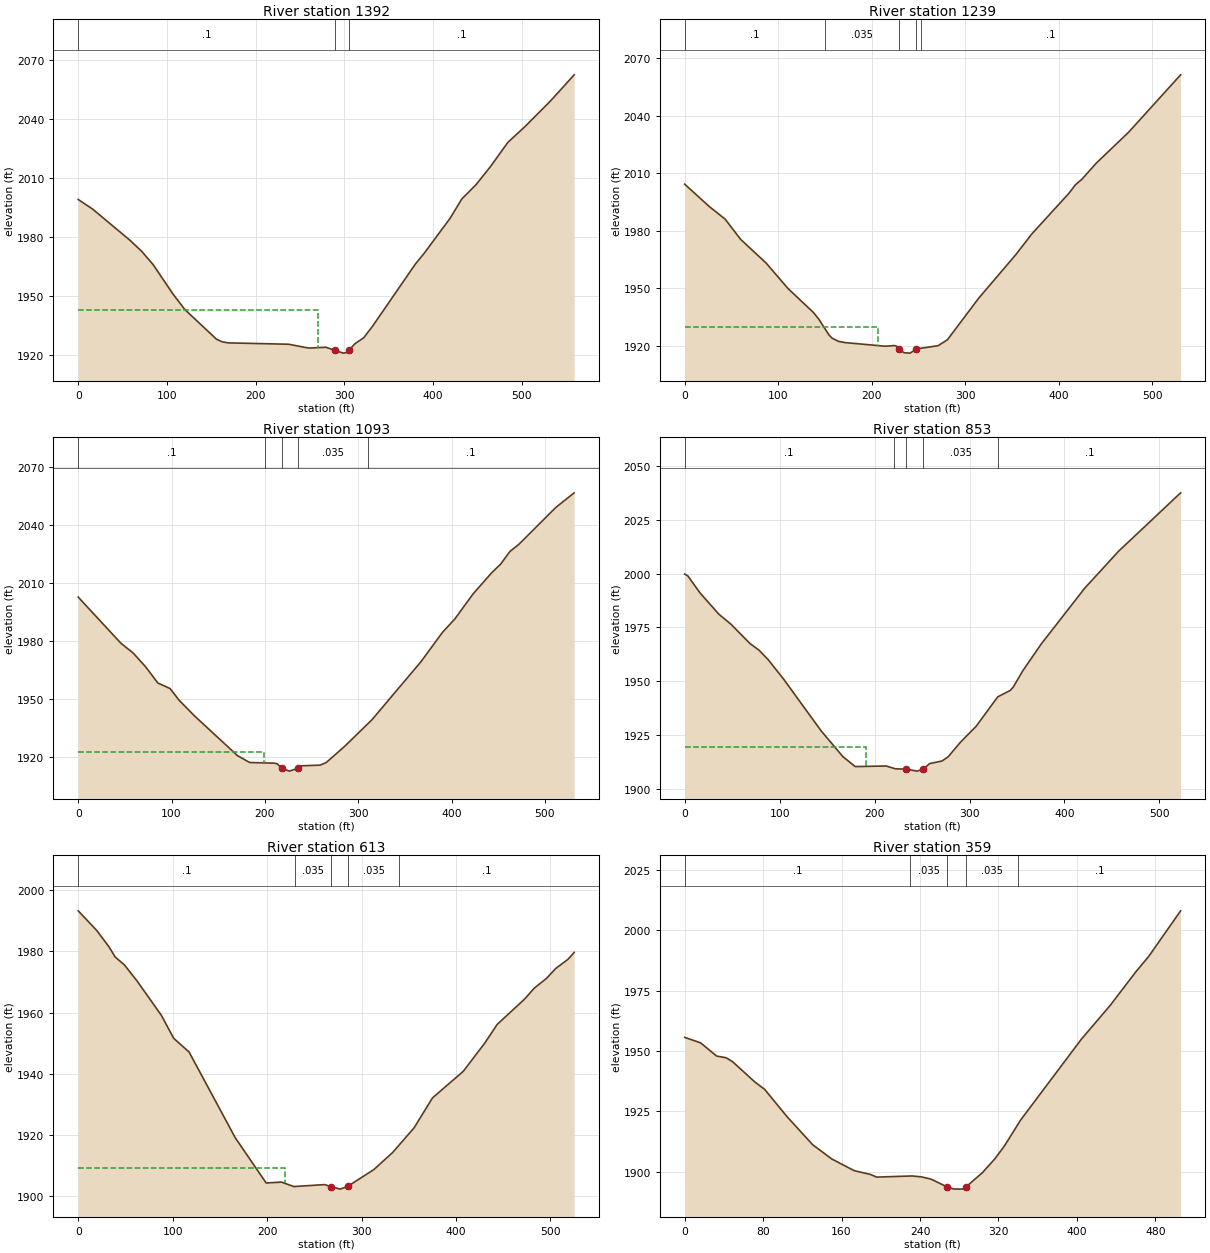
Type RM Length L Ch R = 1 ,1392    ,156.1,152.7,147.1
XS GIS Cut Line= 3
      2085509.57      177383.629     2085539.083      177576.337
     2085502.625       177938.75
#Sta/Elev= 30
       0 1998.92    16.2 1994.05    58.5 1978.11    71.5 1972.58    84.5 1965.77
   107.2 1950.61   120.2 1942.95     156  1927.8   162.5  1926.5     169 1925.97
   237.2 1925.27     260 1923.32   279.5 1923.74   289.3 1922.12     299 1920.75
   302.3 1920.98   305.3  1922.2     312 1925.52   321.8 1928.53   331.6 1934.24
   380.3 1966.15   390.1 1971.54   419.4 1989.38   432.4 1999.11   448.6 2006.46
   464.9 2015.68   484.4 2027.93   503.9 2036.07   533.2 2049.36   559.2 2062.33
#Mann= 3 ,-1 , 0
       0      .1       0   289.3    .045       0   305.3      .1       0
#XS Ineff= 2 , 0
          270.87 1942.45
Permanent Ineff=
       F       F
Bank Sta=289.3,305.3
XS Rating Curve= 0 ,0
Exp/Cntr=0.3,0.1

Type RM Length L Ch R = 1 ,1239    ,150.7,145.9,142.8
XS GIS Cut Line= 4
2085330.04715841177418.5179783682085367.60503489177576.656405641
2085395.27925966177734.7948329132085434.81386648177938.398058027
#Sta/Elev= 30
       0 2004.28    26.3 1992.61    43.2 1986.06      60 1975.41      87 1963.18
   110.6  1949.8   137.6 1937.39   143.3 1933.97   154.5  1925.5   157.8 1923.89
   164.5 1922.26   171.2 1921.63   214.5 1919.72   224.5 1920.08   227.8 1919.54
   229.7  1918.3   234.5 1916.32   241.2 1916.12   247.8  1918.3   271.1    1920
   281.1 1923.11   314.4 1944.72   354.5 1967.67   371.2 1978.24   411.3 1999.66
   417.9 2003.93   424.7 2006.72   440.4 2015.31   474.8 2031.33   530.5 2061.32
#Mann= 5 ,-1 , 0
       0      .1       0     150    .035       0   229.7    .045       0
   247.8    .035       0  252.54      .1       0
#XS Ineff= 2 , 0
          207.16    1930
Permanent Ineff=
       F       F
Bank Sta=229.7,247.8
XS Rating Curve= 0 ,0
Exp/Cntr(USF)=0,0
Exp/Cntr=0.3,0.1

Type RM Length L Ch R = 1 ,1093    ,239.1,240.5,241.5
XS GIS Cut Line= 2
     2085151.931      177478.681     2085358.528      177968.264
#Sta/Elev= 30
       0 2002.55    45.9 1978.65      59 1973.61    72.2 1966.57    85.3 1958.19
    98.4 1955.31   108.2 1949.22   124.6 1941.19   170.6 1920.68   183.7 1917.11
   209.9 1916.77   213.2 1916.44  218.48 1914.03   226.3 1912.65   235.5 1914.13
   239.4  1915.4   259.1 1915.74   265.7 1917.07   285.4 1925.41   314.9 1939.27
   367.4 1969.26   390.3 1984.33   403.5 1991.22   423.1 2004.21   442.8    2015
   452.7 2019.63   462.5 2026.09   472.4 2029.92   511.7 2048.85   531.4 2056.42
#Mann= 5 ,-1 , 0
       0      .1       0     200    .035       0  218.48    .045       0
   235.5    .035       0     310      .1       0
#XS Ineff= 2 , 0
          199.43 1922.59
Permanent Ineff=
       F       F
Bank Sta=218.48,235.5
XS Rating Curve= 0 ,0
Exp/Cntr=0.3,0.1

Type RM Length L Ch R = 1 ,853     ,240.1,240,238.2
XS GIS Cut Line= 2
     2084942.045       177557.22     2085122.851      178047.257
#Sta/Elev= 30
       0 1999.78     3.3 1998.92    16.3 1990.96    35.9 1981.19      49  1976.4
    68.6 1967.62    78.4 1964.42    88.1 1959.98   104.5 1950.85   143.6 1927.09
   166.5 1915.12   179.6 1910.45   212.2 1910.72     222 1909.41   233.4 1909.26
   244.8 1908.34   251.4 1909.24   257.9 1911.84     271 1913.04   277.5    1915
   290.6 1921.84   306.9 1929.11   329.7  1942.8   342.8 1945.76     346  1947.3
   355.8  1954.7   375.4 1967.27   421.1  1993.1     457 2010.38   522.3 2037.46
#Mann= 5 ,-1 , 0
       0      .1       0     220    .035       0   233.4    .045       0
   251.4    .035       0     330      .1       0
#XS Ineff= 2 , 0
          190.83 1919.76
Permanent Ineff=
       F       F
Bank Sta=233.4,251.4
XS Rating Curve= 0 ,0
Exp/Cntr=0.3,0.1

Type RM Length L Ch R = 1 ,613     ,247.9,253.5,251.1
XS GIS Cut Line= 2
     2084699.674      177652.292     2084927.538      178125.382
#Sta/Elev= 30
       0  1993.3    19.6 1986.88    32.6 1981.52    39.1 1978.21    48.9 1975.61
      62 1970.48    88.1 1959.08   101.1 1951.59   117.4 1947.09   166.3 1919.04
     199 1904.26   215.3 1904.53   228.3 1903.08   260.9 1903.72   267.4 1903.09
   277.2 1902.24   285.4 1903.14   313.1 1908.66   332.7 1914.16   355.5 1922.24
   375.1 1932.08   407.7 1940.79   430.5 1950.03   443.6 1956.14   472.9  1964.5
   482.7 1967.96   495.8 1971.18   505.5 1974.42   518.6 1977.44   525.1 1979.69
#Mann= 5 ,-1 , 0
       0      .1       0     230    .035       0   267.4    .045       0
   285.4    .035       0     340      .1       0
#XS Ineff= 2 , 0
           219.2 1909.22
Permanent Ineff=
       F       F
Bank Sta=267.4,285.4
XS Rating Curve= 0 ,0
Exp/Cntr=0.3,0.1

Type RM Length L Ch R = 1 ,359     ,150.4,152.8,152.6
XS GIS Cut Line= 2
     2084506.531      177741.268     2084679.558      178216.535
#Sta/Elev= 30
       0 1955.64    16.3 1953.35    32.6  1947.9    42.4 1947.18      49 1945.52
    71.8 1937.08    81.6  1934.1   104.4 1922.82   130.5 1911.22   150.1 1905.28
     173 1900.45   189.3 1898.92   195.8  1897.8   231.7 1898.27   241.5 1897.89
   251.3 1896.95   267.6 1893.74   274.1  1892.9   280.6 1892.82   283.9 1892.91
   287.2 1893.84   303.5 1899.58   316.5 1905.42   326.3 1910.82   342.6  1921.4
   404.6 1954.89     434 1968.88   460.1 1982.74   473.2 1989.11   505.8 2008.01
#Mann= 5 ,-1 , 0
       0      .1       0     230    .035       0   267.6    .045       0
   287.2    .035       0     340      .1       0
Bank Sta=267.6,287.2
XS Rating Curve= 0 ,0
Exp/Cntr=0.3,0.1

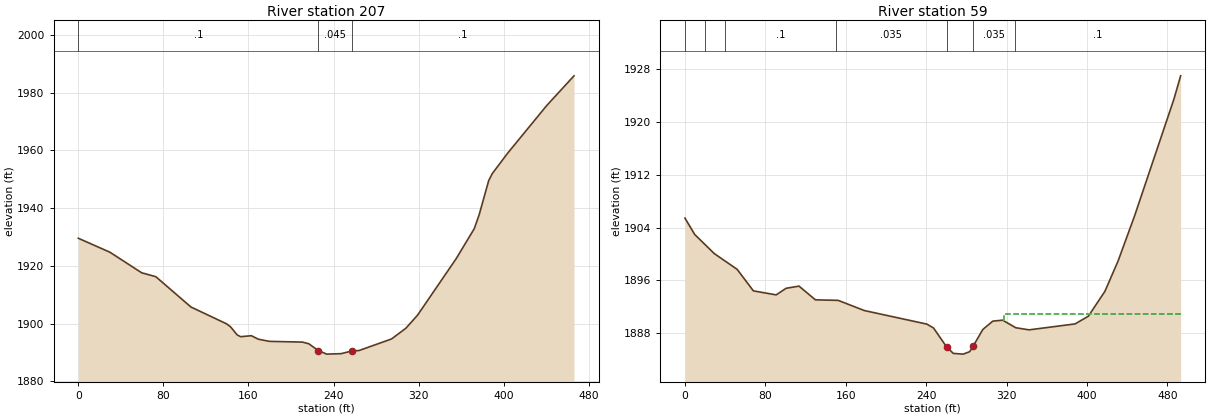
Type RM Length L Ch R = 1 ,207     ,148.9,147.6,142.8
XS GIS Cut Line= 4
2084408.89081955  177792.12001282084436.56504432177960.142091777
2084476.09965114 178118.280519052084509.70406693178246.767991209
#Sta/Elev= 30
       0 1929.54    29.7  1924.7    59.6 1917.57    72.9 1916.22   105.9 1905.72
   139.4 1899.89   143.1 1898.88   149.4 1896.05   152.7 1895.44   162.7 1895.78
   169.3 1894.57   179.7 1893.82   210.7 1893.57   216.7    1893   225.6 1890.64
   233.6  1889.4   247.1 1889.56   257.3 1890.49     264 1890.65   294.5 1894.65
     308 1898.36     319  1902.9   355.3 1922.46   372.3 1932.85   376.9 1937.65
   385.9 1949.52   389.3 1951.95   403.7    1959   440.2  1975.4   466.1  1985.8
#Mann= 3 ,-1 , 0
       0      .1       0   225.6    .045       0   257.3      .1       0
Bank Sta=225.6,257.3
XS Rating Curve= 0 ,0
Exp/Cntr(USF)=0,0
Exp/Cntr=0.3,0.1

Type RM Length L Ch R = 1 ,59      ,70.4,59,47.4
XS GIS Cut Line= 3
     2084339.431      177821.563     2084283.007      177990.834
     2084398.024      178283.803
#Sta/Elev= 30
       0 1905.45     9.7 1902.97    29.2 1900.07    51.9 1897.69    68.1 1894.42
    90.8 1893.81   100.6 1894.81   113.5 1895.14   129.8 1893.06   152.5 1892.98
   178.4 1891.44   240.7 1889.38   247.3  1888.8   260.4 1885.91     267 1884.94
   276.8 1884.83   283.3  1885.2   286.6    1886   296.4 1888.57   306.3 1889.83
   316.1 1889.98   329.2 1888.83   342.4 1888.51   388.2 1889.41   401.4 1890.58
   417.8 1894.33   430.9 1898.92   447.3 1905.75   486.6 1923.52   493.2 1927.02
#Mann= 7 ,-1 , 0
       0      .1       0      20    .035       0      40      .1       0
     150    .035       0   260.4    .045       0   286.6    .035       0
  328.43      .1       0
#XS Ineff= 2 , 0
                          317.34         1890.88
Permanent Ineff=
       F       F
Bank Sta=260.4,286.6
XS Rating Curve= 0 ,0
Exp/Cntr=0.3,0.1
LCMann Table=0

Chan Stop Cuts=-1
Use User Specified Reach Order=0
Composite Channel Slope=5